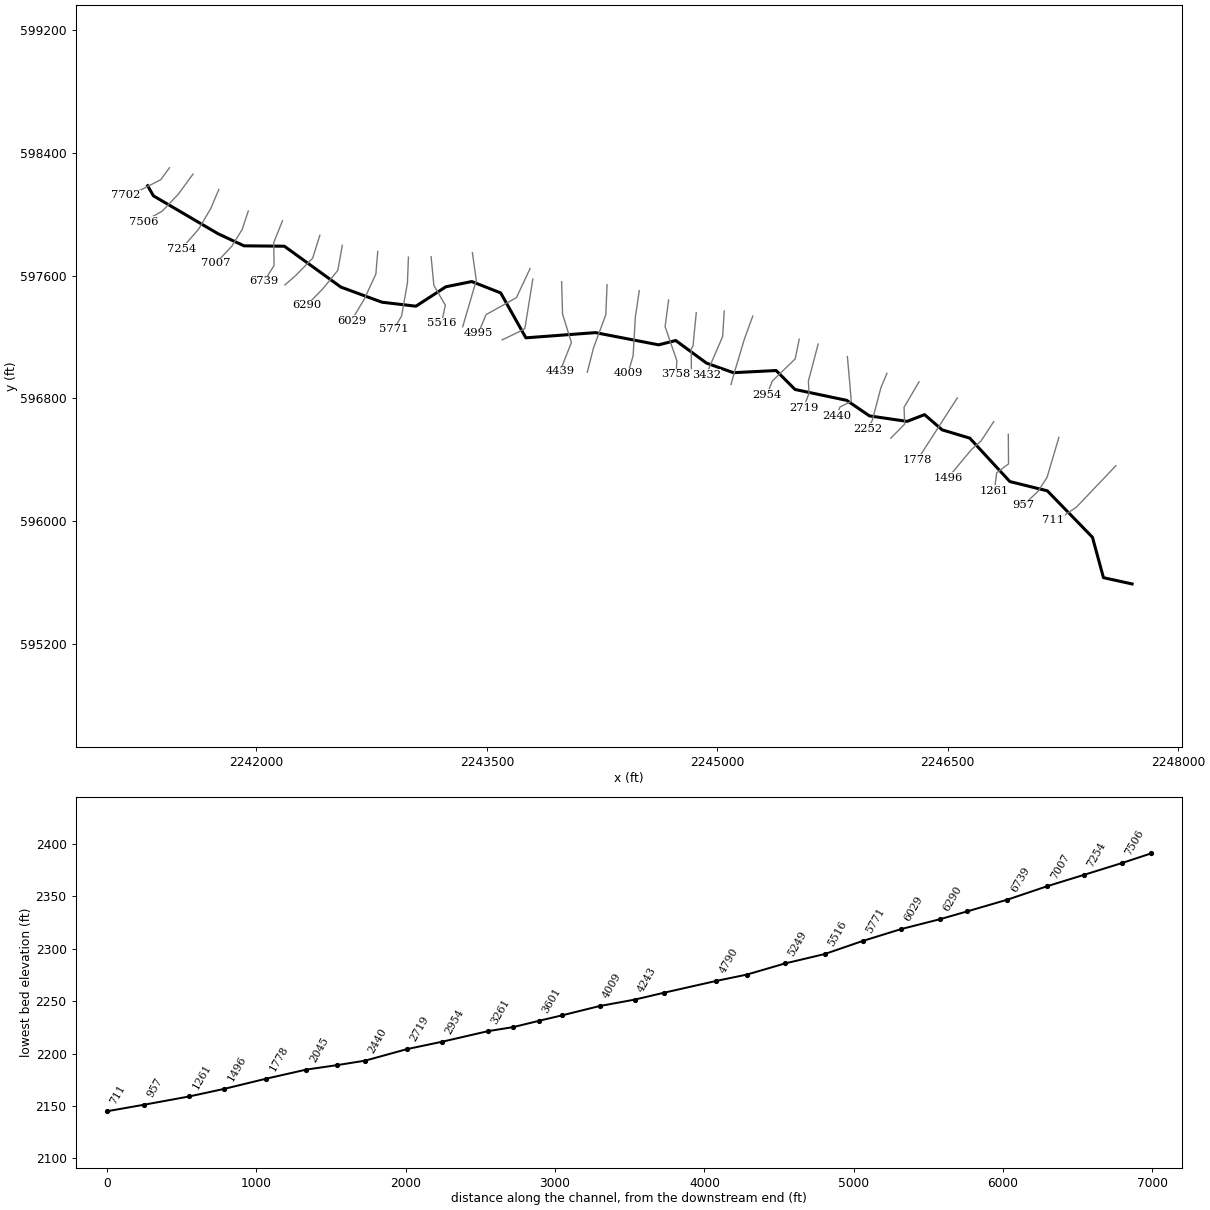
--- HAMILTRN1.prj (project) ---

Proj Title=HAMILTRN1
Current Plan=p01
Default Exp/Contr=0,0
English Units
Geom File=g01
Flow File=f01
Plan File=p01
BEGIN DESCRIPTION:
----------MODEL BY WOOD PLC 2022----------
AFH study
Randolph County, WV
HEC-RAS Version: RAS 6.2
Vertical Datum: NAVD88
Projection: NAD 1983 StatePlane West Virginia S FIPS 4702 (US Feet)
Terrain: 1-meter LIDAR (FEMA Region III 3DEP collected 2016-2018)
Land Use: 2019 NLCD
Hydrologic Method:
WV SIR2010-5033 regression equations
Additional Model Notes:
None
END DESCRIPTION:
DSS Export Rating Curves= 0
DSS Export Rating Curve Sorted= 0
DSS Export Volume Flow Curves= 0
DXF OffsetX= 0
DXF OffsetY= 0
DXF ScaleX= 0
DXF ScaleY= 0

--- HAMILTRN1.p01 (plan) ---

Plan Title=Floodplain
Program Version=4.00
Geom File=g01
Flow File=f01
K Sum by GR=0
Std Step Tol=0.01
Critical Tol=0.01
Num of Std Step Trials=20
Max Error Tol=0.3
Flow Tol Ratio=0.001
Split Flow NTrial=30
Split Flow Tol=0.02
Split Flow Ratio=0.02
Log Output Level=0
Friction Slope Method=1
Unsteady Friction Slope Method=2
Unsteady Bridges Friction Slope Method=1
Global Log Level=0
CheckData=False
Run HTab=0
Run UNet=0
Run PostProcess=0
UNET Theta=0
UNET Theta Warmup=0
UNET ZTol=0
UNET ZSATol=0
UNET MxIter=0
UNET MaxInSteps=0
UNET DtIC=0
UNET DtMin=0
UNET MaxCRTS=0
UNET WFStab=0
UNET SFStab=0
UNET WFX=0
UNET SFX=0
UNET DSS MLevel=0
UNET DZMax Abort=0
UNET Convert EG Bridges=0
UNET Use Existing IB Tables=0
UNET Froude Limit=0
UNET Froude Power=0
Write IC File=0
Echo Input=False
Echo Output=False
Write Detailed=0

--- HAMILTRN1.f01 (steady flow) ---

Flow Title=Flow
Program Version=6.20
Number of Profiles= 1
Profile Names=P100yr
River Rch & RM=HAMILTRN1,Main,7702
     346
River Rch & RM=HAMILTRN1,Main,5249
     419
River Rch & RM=HAMILTRN1,Main,3432
     466
Boundary for River Rch & Prof#=HAMILTRN1,Main            , 1
Up Type= 0
Dn Type= 3
Dn Slope=0.02516
DSS Import GetInterval= 0
DSS Import GetPeak= 0
DSS Import FillOption= 0

--- HAMILTRN1.g01 (geometry) ---

Geom Title=Geometry
Program Version=6.20

River Reach=HAMILTRN1       ,Main
Reach XY= 30
     2241292.075      598185.359     2241329.471      598119.696
     2241751.129      597872.477     2241919.215      597794.114
     2242181.837      597791.611     2242549.585      597525.524
     2242817.213      597426.944     2243038.439      597400.952
     2243232.902      597527.449     2243401.758      597561.528
      2243590.06      597487.401      2243753.91      597194.936
     2244206.567      597228.823     2244617.829      597149.304
     2244729.308      597177.415      2244929.74      597030.123
     2245104.757      596967.933     2245382.782      596981.989
     2245505.814      596858.572     2245841.986      596787.718
     2245990.432      596686.443     2246235.149      596650.823
     2246348.938      596694.722     2246463.498      596595.565
     2246643.137      596541.654     2246904.026      596258.816
     2247147.971      596198.551     2247441.592      595896.267
     2247513.409      595632.874     2247700.014      595591.952

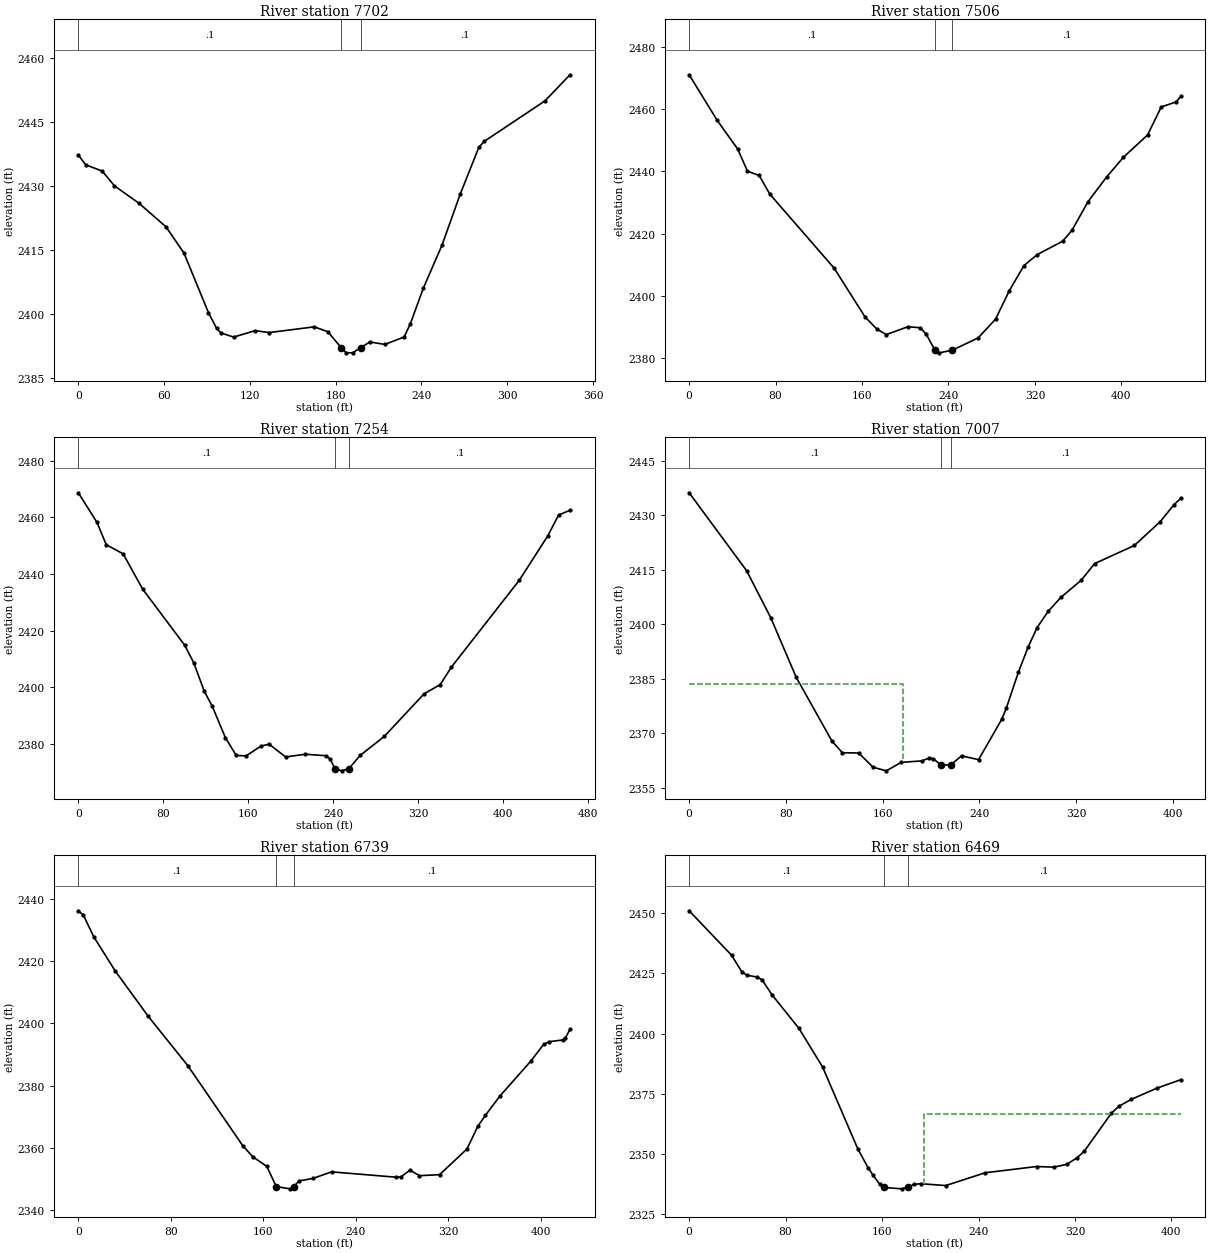
Type RM Length L Ch R = 1 ,7702    ,195.7,195.7,195.7
XS GIS Cut Line= 4
2241434.05737734598302.6255256142241376.97350144598224.556703186
2241242.39045628598155.8464674332241151.67449693598124.246847579
#Sta/Elev= 30
       0 2437.32     5.2 2435.03    16.7 2433.57    25.3  2430.1    42.5 2426.01
    61.3 2420.52    73.9 2414.36      91 2400.42    96.7 2396.71    99.8 2395.63
   108.7 2394.67   123.6 2396.18   133.5 2395.73     165 2397.07   174.5 2395.94
  183.892392.185   187.4 2390.98   191.9    2391  197.452392.185   203.9 2393.53
   214.4 2392.95   227.9 2394.69   232.3 2397.85   241.3 2406.11   254.4 2416.23
   267.1 2428.14   280.2 2439.17   284.1 2440.57   326.4 2450.01   343.9 2456.13
#Mann= 3, -1 ,  0
       0     0.1       0  183.89   0.045       0  197.45     0.1       0
Bank Sta=183.89,197.45
XS Rating Curve= 0 ,0
Exp/Cntr(USF)=0,0
Exp/Cntr=0.3,0.1

Type RM Length L Ch R = 1 ,7506    ,252.8,252.8,252.8
XS GIS Cut Line= 4
2241587.46186832598261.4131064572241490.88556341598129.686236587
2241387.01319272598020.0431786442241264.33016166597951.170286676
#Sta/Elev= 30
       0 2471.05    25.9 2456.44    44.9 2447.22      54 2440.08    64.8 2438.73
    74.7 2432.71   134.2 2408.96   162.8  2393.3   174.1 2389.28   182.6 2387.66
   202.6 2390.18   213.8 2389.82   219.4 2387.79  227.512382.606   231.3 2381.78
  243.382382.608   267.5 2386.57   283.6 2392.61   296.3 2401.72   309.9 2409.81
   322.2 2413.33   345.7 2417.61   354.3 2421.12   369.2 2430.33   386.4 2438.25
   401.9 2444.55   424.3 2451.74   436.9 2460.71   450.7 2462.35455.0635  2464.1
#Mann= 3, -1 ,  0
       0     0.1       0  227.51   0.045       0  243.38     0.1       0
Bank Sta=227.51,243.38
XS Rating Curve= 0 ,0
Exp/Cntr(USF)=0,0
Exp/Cntr=0.3,0.1

Type RM Length L Ch R = 1 ,7254    ,246.7,246.7,246.7
XS GIS Cut Line= 4
2241755.30039658598161.3931639322241702.61084762598036.761596958
2241623.94310768597902.9843707552241510.54202993597773.168340182
#Sta/Elev= 30
       0 2468.69    17.6 2458.22    26.3 2450.36    42.2 2447.15    60.5 2434.74
   100.1 2414.93   108.8 2408.61   118.5 2398.71   126.2 2393.28   138.5 2382.23
   148.7 2375.99     158 2375.86     172 2379.32   179.6 2379.98   195.2 2375.47
   213.7 2376.43   233.2  2375.9   236.9 2374.84  241.572371.382   247.8 2370.57
  254.862371.384   265.4 2376.04     288  2382.7   325.6 2397.78   340.7    2401
   351.2 2407.16   415.1  2437.8   441.9 2453.44   452.2 2460.85462.8766 2462.52
#Mann= 3, -1 ,  0
       0     0.1       0  241.57   0.045       0  254.86     0.1       0
Bank Sta=241.57,254.86
XS Rating Curve= 0 ,0
Exp/Cntr(USF)=0,0
Exp/Cntr=0.3,0.1

Type RM Length L Ch R = 1 ,7007    ,267.9,267.9,267.9
XS GIS Cut Line= 4
2241947.13667831598021.2846065192241907.32626098597901.001020391
2241839.08211344597790.6885627252241736.17729635597681.148916987
#Sta/Elev= 30
       0 2436.25    47.6 2414.76    67.5 2401.86    88.6 2385.43   118.1 2367.92
   126.7 2364.69   140.3 2364.62   152.1  2360.7   163.1 2359.71   175.4 2362.05
   192.3 2362.44   198.6 2363.22   201.7 2363.08   208.4 2361.32   216.3 2361.33
   225.3 2363.83   239.4 2362.79   258.5 2373.85   262.4 2376.99   272.3 2386.82
   280.4 2393.79   287.8 2399.12   296.9 2403.58   307.6  2407.5   324.3 2412.16
   335.3 2416.74   368.3 2421.75   389.7 2428.31     401 2432.97406.7101 2434.73
#Mann= 3, -1 ,  0
       0     0.1       0   208.4   0.045       0   216.3     0.1       0
#XS Ineff= 2 , 0
           176.9 2383.62
Permanent Ineff=
       F       F
Bank Sta=208.4,216.3
XS Rating Curve= 0 ,0
Exp/Cntr(USF)=0,0
Exp/Cntr=0.3,0.1

Type RM Length L Ch R = 1 ,6739    ,269.8,269.8,269.8
XS GIS Cut Line= 4
2242169.53752368597957.2854737292242112.72250855597815.386024293
2242114.64607097597665.3481555292242048.98207506597561.860235825
#Sta/Elev= 30
       0  2436.2     4.4  2434.8    13.4 2427.81    31.9 2416.87    60.4 2402.33
    94.9 2386.34   142.3 2360.69   150.9 2357.15   163.1 2354.04  171.27 2347.56
   183.1 2346.82  186.322347.561   191.1 2349.36   203.1 2350.17   219.1 2352.28
   275.1 2350.56   279.1 2350.66   287.1 2352.84   295.1 2351.05   312.6 2351.37
   336.3 2359.62   345.7 2366.92   352.3 2370.46   364.7  2376.6   391.8 2387.98
   402.6 2393.24   407.3  2394.1   419.5  2394.7   421.5  2395.3425.4634 2398.12
#Mann= 3, -1 ,  0
       0     0.1       0  171.27   0.045       0  186.32     0.1       0
Bank Sta=171.27,186.32
XS Rating Curve= 0 ,0
Exp/Cntr(USF)=0,0
Exp/Cntr=0.3,0.1

Type RM Length L Ch R = 1 ,6469    ,179.3,179.3,179.3
XS GIS Cut Line= 4
2242412.82775692597862.7790505022242366.01530112597713.574174526
2242259.57818054597604.5723040562242185.18300454597539.203925826
#Sta/Elev= 30
       0 2450.89    35.2 2432.45    43.6 2425.64    47.8 2424.17    56.2 2423.44
    60.4  2422.3    68.8 2416.01    91.1 2402.11   110.7 2386.09     140 2352.05
   148.4 2344.37   152.6  2341.2     158 2337.55  161.542336.175   176.2  2335.6
  181.132336.173   186.2 2337.42   191.9 2337.74   212.8 2336.96   245.6 2342.27
   288.1 2344.85   302.3  2344.6   313.3 2345.75     322 2348.58   327.7  2351.2
   350.2 2366.97   356.3 2369.79   366.5 2372.65   387.8 2377.31   407.8 2380.86
#Mann= 3, -1 ,  0
       0     0.1       0  161.54   0.045       0  181.13     0.1       0
#XS Ineff= 2 , 0
                          194.58         2366.59
Permanent Ineff=
       F       F
Bank Sta=161.54,181.13
XS Rating Curve= 0 ,0
Exp/Cntr(USF)=0,0
Exp/Cntr=0.3,0.1

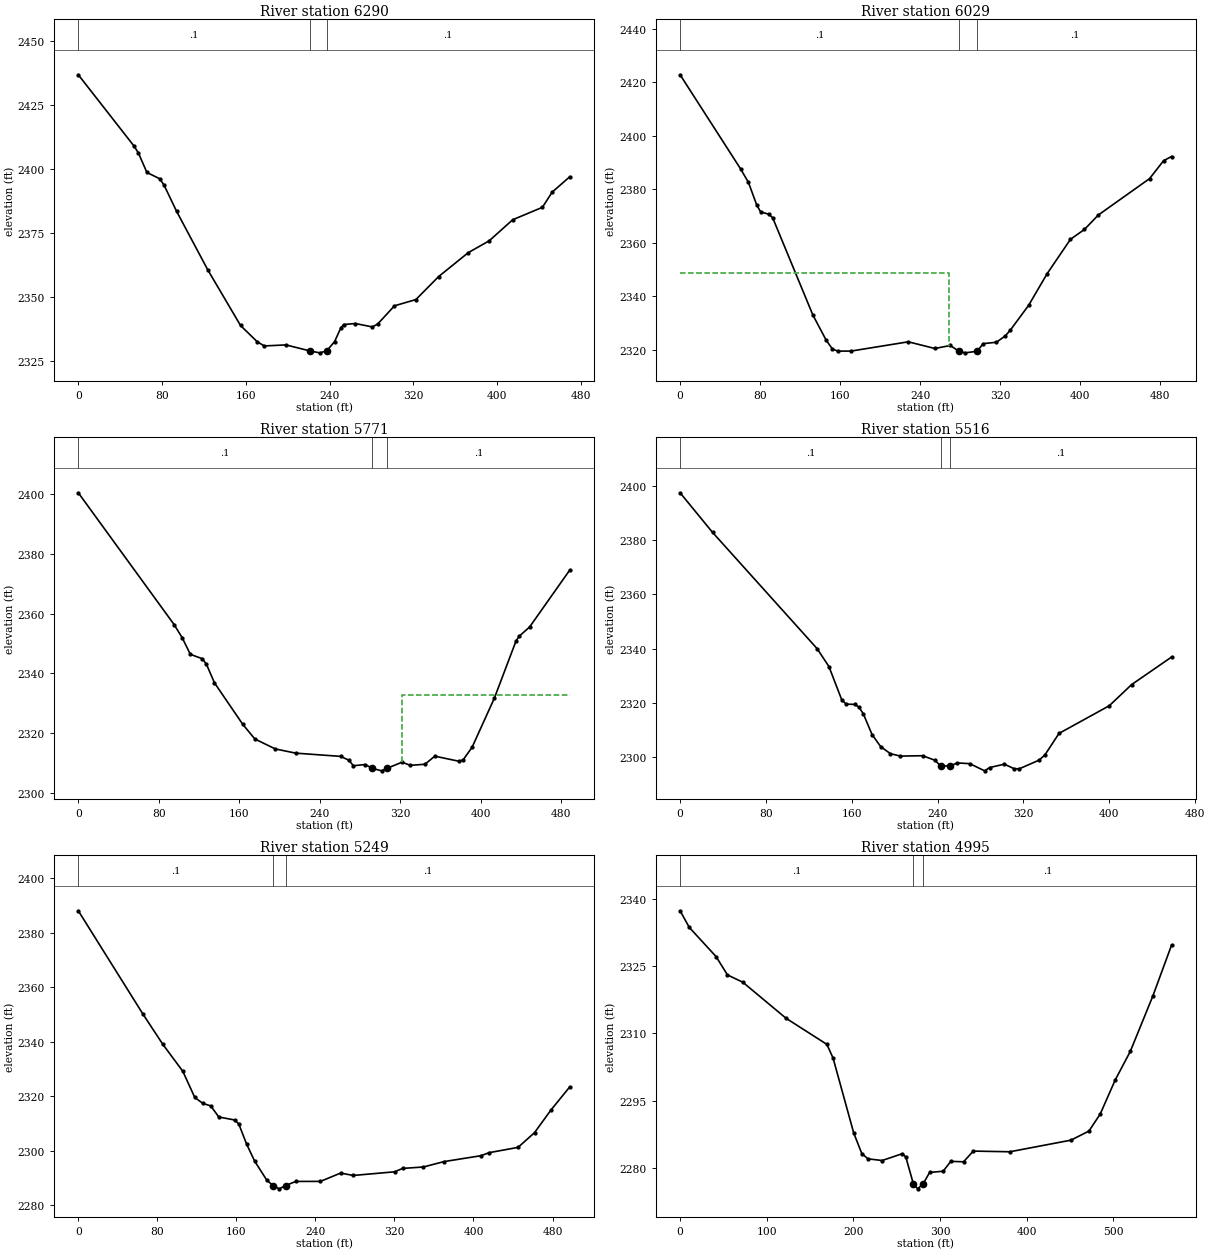
Type RM Length L Ch R = 1 ,6290    ,261.4,261.4,261.4
XS GIS Cut Line= 4
2242559.01292807  597797.66336332242529.78433353597634.067802548
2242433.60621253 597515.804335242242328.49293393597407.972562933
#Sta/Elev= 30
       0 2436.97    53.3 2409.05    57.4 2406.37    65.5 2398.79    77.7 2396.32
    81.8  2393.9    93.9 2383.55   123.5 2360.79   154.9 2338.95   170.8 2332.61
   177.6 2330.96   198.3 2331.36  220.892329.035   230.5 2328.26  237.212329.035
   244.7 2332.65   250.4 2337.78   253.3 2339.33   264.6 2339.72   280.8 2338.38
   285.9 2339.55   301.9 2346.65   322.3 2349.08   344.1  2358.1   372.4 2367.45
   392.2 2372.02   414.8  2380.3   443.1 2385.15   452.5 2391.11   469.2 2397.08
#Mann= 3, -1 ,  0
       0     0.1       0  220.89   0.045       0  237.21     0.1       0
Bank Sta=220.89,237.21
XS Rating Curve= 0 ,0
Exp/Cntr(USF)=0,0
Exp/Cntr=0.3,0.1

Type RM Length L Ch R = 1 ,6029    ,257.3,257.3,257.3
XS GIS Cut Line= 4
2242789.63087357597757.3857119342242777.53805841597610.794452395
2242703.26546586597449.5447448762242618.09150042597306.394717858
#Sta/Elev= 30
       0 2422.88    60.4 2387.69    68.3 2382.62    76.5 2374.22    80.5 2371.53
    88.5 2370.71    92.5 2369.38   132.7 2332.96   146.1 2323.46   152.3 2320.21
   157.7 2319.44   170.9 2319.45   228.1 2322.92   254.6 2320.42   270.1 2321.54
  278.642319.386     285 2318.79  296.892319.386     303 2322.23   316.2 2322.76
     325 2325.12   330.1  2327.3   348.3 2336.53   366.9 2348.44   390.2 2361.29
   404.2 2364.99   418.1  2370.4   469.3 2384.02   483.3 2390.73491.1949 2392.28
#Mann= 3, -1 ,  0
       0     0.1       0  278.64   0.045       0  296.89     0.1       0
#XS Ineff= 2 , 0
          268.59 2348.76
Permanent Ineff=
       F       F
Bank Sta=278.64,296.89
XS Rating Curve= 0 ,0
Exp/Cntr(USF)=0,0
Exp/Cntr=0.3,0.1

Type RM Length L Ch R = 1 ,5771    ,255,255,255
XS GIS Cut Line= 4
2242989.36017325 597720.357050392242983.02360255597552.636078442
2242944.79006553597337.2244216642242892.90343085 597249.84945639
#Sta/Elev= 30
       0 2400.33    95.2 2356.31   103.3 2351.88   111.3 2346.38   123.3 2344.89
   127.3 2343.06   135.3 2336.85   163.3 2323.04   175.4  2318.1   195.7 2314.78
     216 2313.37   260.7 2312.29   268.9 2310.99   273.3 2309.16   285.1 2309.57
  292.082308.295   301.4 2307.46  306.672308.296   321.7 2310.35   329.8 2309.29
   344.4 2309.66   354.2 2312.36   378.5 2310.64   382.6 2311.24   391.3 2315.37
   413.4 2331.75   434.8 2350.75   437.8 2352.34   448.4 2355.51 488.239 2374.49
#Mann= 3, -1 ,  0
       0     0.1       0  292.08   0.045       0  306.67     0.1       0
#XS Ineff= 2 , 0
                          322.02          2332.9
Permanent Ineff=
       F       F
Bank Sta=292.08,306.67
XS Rating Curve= 0 ,0
Exp/Cntr(USF)=0,0
Exp/Cntr=0.3,0.1

Type RM Length L Ch R = 1 ,5516    ,267.1,267.1,267.1
XS GIS Cut Line= 4
2243137.08741526597723.2321609832243154.95225308597536.387506376
2243229.71348111597407.0945590742243204.45611721 597288.85806663
#Sta/Elev= 30
       0 2397.36    30.2 2382.79   127.7 2339.95   138.7 2333.36   150.7 2321.05
   154.8 2319.53   162.8 2319.41   166.8 2318.37   170.8  2315.9   178.9 2308.31
   186.9 2303.88     196 2301.27   205.3 2300.38   226.1 2300.52   237.6 2298.82
  242.74 2296.74  251.86 2296.75   258.3 2297.87     270 2297.59   283.8 2294.95
   288.4 2296.16   302.2  2297.4   311.5  2295.7   316.2 2295.72   334.6  2298.9
     340 2300.82   353.1 2308.73     400 2318.94   420.8 2326.72457.9525 2336.85
#Mann= 3, -1 ,  0
       0     0.1       0  242.74   0.045       0  251.86     0.1       0
Bank Sta=242.74,251.86
XS Rating Curve= 0 ,0
Exp/Cntr(USF)=0,0
Exp/Cntr=0.3,0.1

Type RM Length L Ch R = 1 ,5249    ,254.3,254.3,254.3
XS GIS Cut Line= 3
 2243405.7858589597749.9820396842243431.06113277597569.229828094
2243342.69348743597266.999275509
#Sta/Elev= 30
       0 2388.13    65.4 2350.18    85.6 2339.02   105.8 2329.13   117.9 2319.51
     126 2317.35   134.1  2316.4   142.2 2312.34   158.3 2311.23   162.4 2309.81
   170.4 2302.34   178.5 2296.12   190.9 2289.06  197.192287.145   203.4 2285.93
  209.962287.145   220.1 2288.65   245.1 2288.67   265.5 2291.72   278.4 2290.85
   320.1 2292.19   328.4 2293.44   349.3 2293.96   370.1 2295.94   407.6 2298.11
   415.9 2299.23   445.1 2301.17   461.8 2306.59   478.3 2314.84   497.4 2323.39
#Mann= 3, -1 ,  0
       0     0.1       0  197.19   0.045       0  209.96     0.1       0
Bank Sta=197.19,209.96
XS Rating Curve= 0 ,0
Exp/Cntr(USF)=0,0
Exp/Cntr=0.3,0.1

Type RM Length L Ch R = 1 ,4995    ,204.5,204.5,204.5
XS GIS Cut Line= 4
2243781.31057006597646.7504869122243692.48902246 597456.68172821
2243494.59165414597345.8592019512243444.24626985597225.301443103
#Sta/Elev= 30
       0 2337.37    10.6 2333.66    41.5 2327.16    54.7 2323.06    72.4 2321.43
   122.4 2313.38   169.5 2307.56   176.6 2304.51   200.4 2287.82   209.8 2283.19
     217 2282.03   233.2 2281.66   256.7 2283.19   260.6 2282.43  269.212276.509
   274.3 2275.34  280.692276.508   288.1    2279   303.7 2279.27   312.5 2281.47
   327.2 2281.37   338.5 2283.76   380.7 2283.61   451.2  2286.2     472 2288.23
     485 2292.03   502.4 2299.66   519.7 2305.99   545.7 2318.33   567.3 2329.68
#Mann= 3, -1 ,  0
       0     0.1       0  269.21   0.045       0  280.69     0.1       0
Bank Sta=269.21,280.69
XS Rating Curve= 0 ,0
Exp/Cntr(USF)=0,0
Exp/Cntr=0.3,0.1

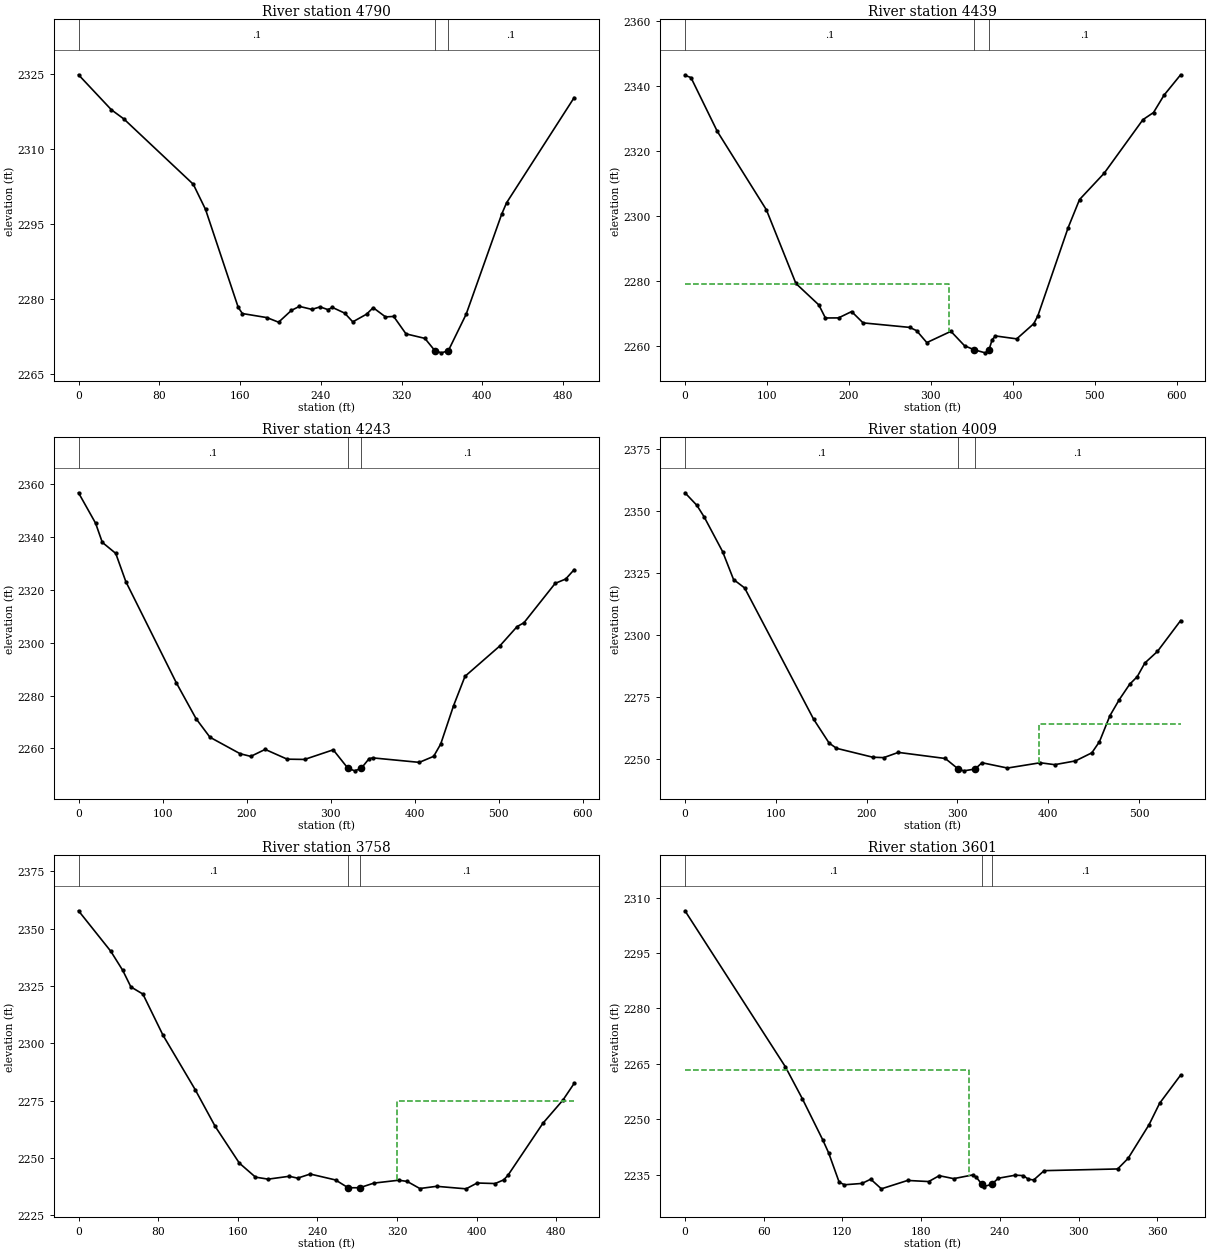
Type RM Length L Ch R = 1 ,4790    ,351.1,351.1,351.1
XS GIS Cut Line= 4
2243799.17979411597577.4017973362243747.33010685597255.724764098
2243703.87650221597231.721975865 2243599.7875547597181.507978662
#Sta/Elev= 30
       0 2324.86    32.6 2317.86    44.8 2316.06   113.7 2302.99   125.8 2297.98
   158.2 2278.41   162.3 2277.17   186.6 2276.36   198.2 2275.44   210.9  2277.8
   218.8  2278.6   231.2    2278   239.3  2278.5   247.1 2277.95   251.4  2278.4
   263.6 2277.26   271.7 2275.51   285.4 2277.05   291.9 2278.34   304.1  2276.5
   312.2 2276.59   324.4 2273.11   343.1 2272.21352.9501 2269.77   359.5 2269.32
366.33012269.739     384 2277.03   419.1 2296.96     424 2299.28     491  2320.3
#Mann= 3, -1 ,  0
       0     0.1       0352.9501   0.045       0366.3301     0.1       0
Bank Sta=352.9501,366.3301
XS Rating Curve= 0 ,0
Exp/Cntr(USF)=0,0
Exp/Cntr=0.3,0.1

Type RM Length L Ch R = 1 ,4439    ,195.8,195.8,195.8
XS GIS Cut Line= 4
2243986.51024596597560.520293484 2243992.6417485597349.238621691
2244050.30073482 597164.534411262243976.79900097596978.375725526
#Sta/Elev= 30
       0 2343.41     7.3 2342.72    39.4 2326.18    99.4 2302.01   135.4 2279.36
   163.4 2272.75   171.4 2268.74   187.4 2268.76   203.4 2270.71   217.4 2267.23
   274.3 2265.84   282.7 2264.84   295.2 2261.16   324.6 2264.63   341.3 2260.18
  353.382258.924   366.5 2258.01  371.072258.923   374.9 2262.03     379 2263.21
   404.9 2262.31   425.7 2266.97   430.7 2269.38   467.7 2296.53   481.6 2305.18
   511.7 2313.29     559 2329.77   571.9 2331.96   584.8 2337.32605.0092 2343.58
#Mann= 3, -1 ,  0
       0     0.1       0  353.38   0.045       0  371.07     0.1       0
#XS Ineff= 2 , 0
          322.45  2279.1
Permanent Ineff=
       F       F
Bank Sta=353.38,371.07
XS Rating Curve= 0 ,0
Exp/Cntr(USF)=0,0
Exp/Cntr=0.3,0.1

Type RM Length L Ch R = 1 ,4243    ,234.6,234.6,234.6
XS GIS Cut Line= 4
2244282.19146064597541.4588403452244274.38522935597345.635782208
2244194.24901107597129.6589012272244153.70493575596971.354620596
#Sta/Elev= 30
       0  2356.8    20.3 2345.29    28.3 2338.02    44.3 2333.84    56.3 2323.16
   116.4 2284.81   139.9 2271.22   156.4  2264.2   192.4 2257.94     205 2256.95
   222.1 2259.59   248.3 2255.89     269 2255.79   303.1 2259.43  320.542252.462
   328.7 2251.47  336.522252.462   345.8 2256.09   350.1 2256.38   405.5 2254.68
   422.6 2256.96     431 2261.63   446.3 2276.16   459.9 2287.27   501.2 2298.74
   521.8 2306.08   530.1 2307.59   567.2 2322.48   579.7 2324.13   589.8 2327.68
#Mann= 3, -1 ,  0
       0     0.1       0  320.54   0.045       0  336.52     0.1       0
Bank Sta=320.54,336.52
XS Rating Curve= 0 ,0
Exp/Cntr(USF)=0,0
Exp/Cntr=0.3,0.1

Type RM Length L Ch R = 1 ,4009    ,251.4,251.4,251.4
XS GIS Cut Line= 4
2244491.91697938597502.1530864322244466.08612848597326.610668953
2244451.83751796597078.0515743432244418.35176885596963.337829708
#Sta/Elev= 30
       0 2357.48    13.1 2352.42    21.2 2347.69    41.4 2333.78    53.5 2322.49
    65.7  2319.1   141.6 2266.21   158.7 2256.56   166.8 2254.43   206.9 2250.82
   218.9 2250.66     235 2252.77   286.7 2250.31  300.98 2246.06   307.1 2245.33
  319.56 2246.06   327.1  2248.6   355.2 2246.46   391.2 2248.59   407.2 2247.82
   430.1 2249.34   448.1  2252.6   456.5 2257.08     468 2267.56   478.4 2274.09
   489.8 2280.27   498.1  2283.3   506.5 2288.82   520.4 2293.51545.9011 2305.94
#Mann= 3, -1 ,  0
       0     0.1       0  300.98   0.045       0  319.56     0.1       0
#XS Ineff= 2 , 0
                          390.32         2264.21
Permanent Ineff=
       F       F
Bank Sta=300.98,319.56
XS Rating Curve= 0 ,0
Exp/Cntr(USF)=0,0
Exp/Cntr=0.3,0.1

Type RM Length L Ch R = 1 ,3758    ,156.4,156.4,156.4
XS GIS Cut Line= 4
2244683.02206673597441.3324424592244660.05943044597267.843402166
2244736.57974619597046.1983496482244731.57662855596957.837282993
#Sta/Elev= 30
       0 2357.85    32.4 2340.19    44.5 2331.79    52.6 2324.62    64.7 2321.48
    84.9 2303.51   117.2 2279.79   137.3 2263.73   161.6 2247.69   177.8 2241.57
   190.5 2240.69   211.7 2241.94   220.1 2241.13   232.8 2242.92   258.2 2240.34
   270.9 2236.93   282.5 2236.94   296.7 2238.96   321.7 2240.22   330.2  2239.7
   342.9  2236.6   359.8 2237.56   389.4 2236.46   400.5 2239.01   418.6 2238.77
   427.1 2240.36   431.4 2242.33   466.6  2265.1   486.7 2275.21497.9868  2282.5
#Mann= 3, -1 ,  0
       0     0.1       0   270.9   0.045       0   282.5     0.1       0
#XS Ineff= 2 , 0
                          319.86         2274.79
Permanent Ineff=
       F       F
Bank Sta=270.9,282.5
XS Rating Curve= 0 ,0
Exp/Cntr(USF)=0,0
Exp/Cntr=0.3,0.1

Type RM Length L Ch R = 1 ,3601    ,169.2,169.2,169.2
XS GIS Cut Line= 5
2244863.05851508597358.0837598012244848.95756919597218.484395526
2244841.90709625597140.9291931512244829.92129224597124.008058087
2244831.33138683596985.113741107
#Sta/Elev= 30
       0 2306.43    76.5 2264.23    89.4 2255.62   105.1 2244.38   109.5 2240.93
   117.5 2233.02   121.5 2232.29   134.9 2232.65   141.6  2233.8   149.7 2231.19
   169.7 2233.46   185.8 2233.16   193.8 2234.75   204.8 2233.95   219.2 2234.94
   222.1 2234.32  226.29 2232.43   228.1 2231.82  233.79 2232.43   238.9 2234.06
   251.9 2234.89   257.8 2234.77   261.8  2233.8   265.8 2233.59   273.8 2236.11
   329.8 2236.57   337.8 2239.44   353.8 2248.58   361.8 2254.34377.8223 2261.97
#Mann= 3, -1 ,  0
       0     0.1       0  226.29   0.045       0  233.79     0.1       0
#XS Ineff= 2 , 0
          216.85 2263.47
Permanent Ineff=
       F       F
Bank Sta=226.29,233.79
XS Rating Curve= 0 ,0
Exp/Cntr(USF)=0,0
Exp/Cntr=0.3,0.1

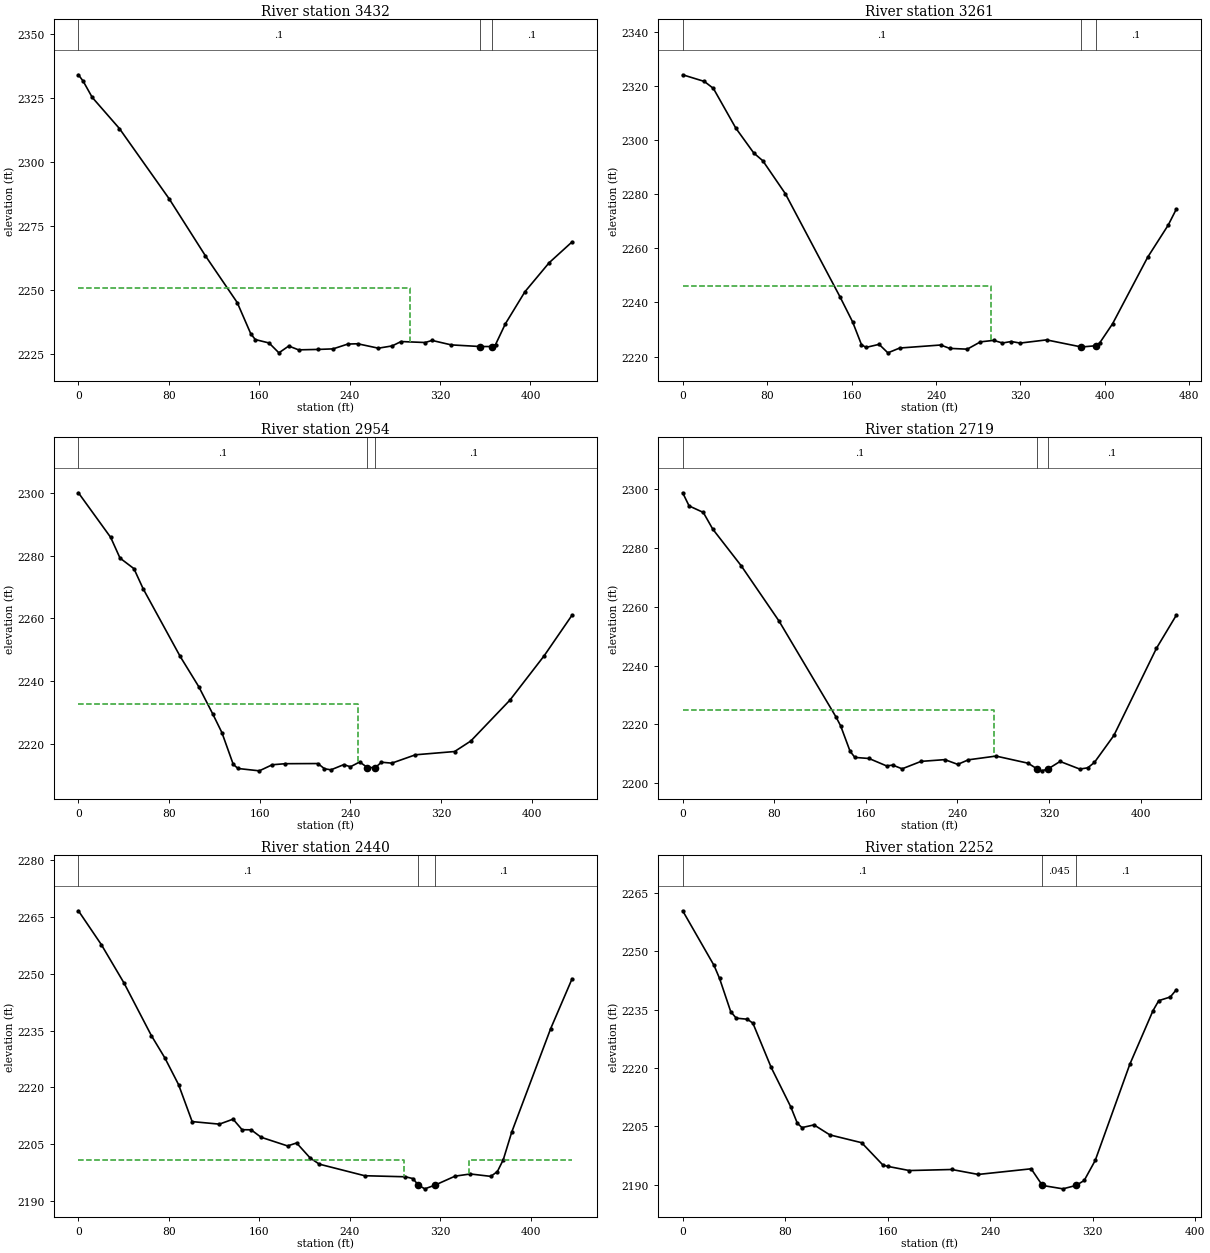
Type RM Length L Ch R = 1 ,3432    ,170.6,170.6,170.6
XS GIS Cut Line= 4
2245045.06480913597369.356449859  2245034.462565597202.903061224
2244953.07910688597014.4424039992244928.06316159596954.786537781
#Sta/Elev= 30
       0 2334.11     4.2 2331.61    12.2 2325.28    36.3 2313.06    80.3 2285.56
   112.4 2263.23   140.5 2244.97   152.5 2232.75   156.5 2230.47   168.7 2229.13
   177.4 2225.27   186.1 2227.94   194.8 2226.44   212.2 2226.61   225.3 2226.82
   238.4 2228.71   247.1 2228.82   265.4 2227.09   277.6 2227.98   285.5 2229.69
   306.8 2229.31   312.9 2230.13   329.9 2228.38   355.5 2227.74  365.92 2227.74
   369.1 2228.52   377.8 2236.64   395.1 2249.19   416.5 2260.53   436.8 2268.69
#Mann= 3, -1 ,  0
       0     0.1       0   355.5   0.045       0  365.92     0.1       0
#XS Ineff= 2 , 0
          293.67  2250.6
Permanent Ineff=
       F       F
Bank Sta=355.5,365.92
XS Rating Curve= 0 ,0
Exp/Cntr(USF)=0,0
Exp/Cntr=0.3,0.1

Type RM Length L Ch R = 1 ,3261    ,307.6,307.6,307.6
XS GIS Cut Line= 4
2245230.71966078597336.4771861722245177.01696189597189.622789655
2245108.33045706596960.2471993352245088.76365071596891.016987683
#Sta/Elev= 30
       0 2324.23    20.5 2321.77    29.1 2319.18    50.4 2304.46    67.4 2295.27
    75.9 2292.43    97.2 2280.28     149 2242.13     161 2232.81   169.4 2224.39
   173.7 2223.38   186.1 2224.51   194.4 2221.37   205.6 2223.15   244.5 2224.27
   252.9 2223.02   269.6 2222.73   282.1 2225.43   294.6 2225.98     303 2225.01
   311.3 2225.56   319.7 2224.98   344.7 2226.16377.7219 2223.54391.58672223.996
   395.2  2225.1   407.3 2232.13   440.5 2256.71     460 2268.62   467.7 2274.54
#Mann= 3, -1 ,  0
       0     0.1       0377.7219   0.045       0391.5867     0.1       0
#XS Ineff= 2 , 0
          291.69 2245.93
Permanent Ineff=
       F       F
Bank Sta=377.7219,391.5867
XS Rating Curve= 0 ,0
Exp/Cntr(USF)=0,0
Exp/Cntr=0.3,0.1

Type RM Length L Ch R = 1 ,2954    ,235,235,235
XS GIS Cut Line= 4
2245533.01543798597185.136505782 2245506.6291222597057.602646197
   2245357.98621596913.3574532882245321.30467507596822.280380633
#Sta/Elev= 30
       0 2300.12    28.5 2285.85    36.7 2279.25      49 2275.87    57.1 2269.46
    89.8 2247.82   106.2 2238.15   118.4 2229.54   126.6 2223.49   136.6 2213.35
   140.8 2212.02   159.6 2211.27     171 2213.21   182.5 2213.55   211.3  2213.6
   217.1 2211.94   222.8 2211.59   234.1 2213.25     240 2212.57   248.2 2214.11
     255 2212.31   261.9 2212.31   267.4 2214.02   276.5 2213.73   297.4  2216.4
   331.9 2217.44   346.2  2220.8   380.7 2233.86   410.9 2248.03435.5478 2261.02
#Mann= 3, -1 ,  0
       0     0.1       0     255   0.045       0   261.9     0.1       0
#XS Ineff= 2 , 0
          246.47 2232.71
Permanent Ineff=
       F       F
Bank Sta=255,261.9
XS Rating Curve= 0 ,0
Exp/Cntr(USF)=0,0
Exp/Cntr=0.3,0.1

Type RM Length L Ch R = 1 ,2719    ,279.3,279.3,279.3
XS GIS Cut Line= 4
2245656.29425568597154.6074488872245592.84222309 596913.34088392
2245596.80017046596833.390347119 2245560.7826772596738.233382692
#Sta/Elev= 30
       0 2298.79     5.6 2294.32      18 2292.11    26.3 2286.42    51.1 2273.98
    84.2 2255.15   133.8 2222.65     138 2219.54   146.2 2210.93   150.4  2208.8
   162.8 2208.43   178.1 2205.91   183.5 2206.18   191.7 2204.92   208.3 2207.45
     229 2208.04   240.3 2206.43   249.6 2207.98   273.7 2209.25   301.7 2206.83
   309.7 2204.87   313.7 2204.23  319.15 2204.87   329.7 2207.42   346.9 2204.83
   353.9 2205.26   359.7 2207.09   376.7 2216.26   413.9 2245.91431.2646 2257.17
#Mann= 3, -1 ,  0
       0     0.1       0   309.7   0.045       0  319.15     0.1       0
#XS Ineff= 2 , 0
          271.62 2224.87
Permanent Ineff=
       F       F
Bank Sta=309.7,319.15
XS Rating Curve= 0 ,0
Exp/Cntr(USF)=0,0
Exp/Cntr=0.3,0.1

Type RM Length L Ch R = 1 ,2440    ,188,188,188
XS GIS Cut Line= 5
2245846.48563097597073.4170742662245862.62507194596893.239083525
2245871.77207191596781.1139857822245798.06529357596744.284433963
2245777.40348918596687.026704646
#Sta/Elev= 30
       0  2266.6    20.3 2257.66    40.4 2247.51    64.5 2233.69    76.5 2227.76
    88.6 2220.73   100.6 2210.98   124.7 2210.31   136.8 2211.62   144.8 2208.84
   152.8 2208.81   161.6 2206.85     185 2204.56     193 2205.34     205 2201.38
   213.1 2199.75   253.2  2196.7   289.3 2196.42     296 2195.94  300.542194.245
   306.4 2193.24  315.642194.247   333.2 2196.59   346.7 2197.16   364.8 2196.53
   370.6  2197.8   375.8 2200.91   383.3 2208.22   417.7 2235.48436.6646 2248.65
#Mann= 3, -1 ,  0
       0     0.1       0  300.54   0.045       0  315.64     0.1       0
#XS Ineff= 2 , 0
          288.04 2200.75  345.32         2200.96
Permanent Ineff=
       F       F
Bank Sta=300.54,315.64
XS Rating Curve= 0 ,0
Exp/Cntr(USF)=0,0
Exp/Cntr=0.3,0.1

Type RM Length L Ch R = 1 ,2252    ,206.4,206.4,206.4
XS GIS Cut Line= 4
2246103.89224461596963.786459185 2246064.1565809596868.172587979
2246009.86375008596660.7739742652245978.79632421596600.983342311
#Sta/Elev= 30
       0 2260.41    24.5 2246.35    28.8 2243.01    37.5 2234.49    41.8 2232.82
    50.5 2232.54    54.8 2231.53    69.1 2220.14    84.4    2210    89.5 2205.81
    93.1  2204.7   102.5 2205.39   114.9 2202.82   139.7 2200.81   156.3 2195.07
   160.4 2194.71   176.9 2193.66     210 2193.93   230.7 2192.66     272 2194.11
  280.762189.836   296.8 2188.96  307.042189.836   313.4 2191.11     322 2196.26
     349 2220.97   367.1 2234.75   371.6 2237.32   380.6 2238.26385.3095 2240.13
#Mann= 3, -1 ,  0
       0     0.1       0  280.76   0.045       0  307.04     0.1       0
Bank Sta=280.76,307.04
XS Rating Curve= 0 ,0
Exp/Cntr(USF)=0,0
Exp/Cntr=0.3,0.1

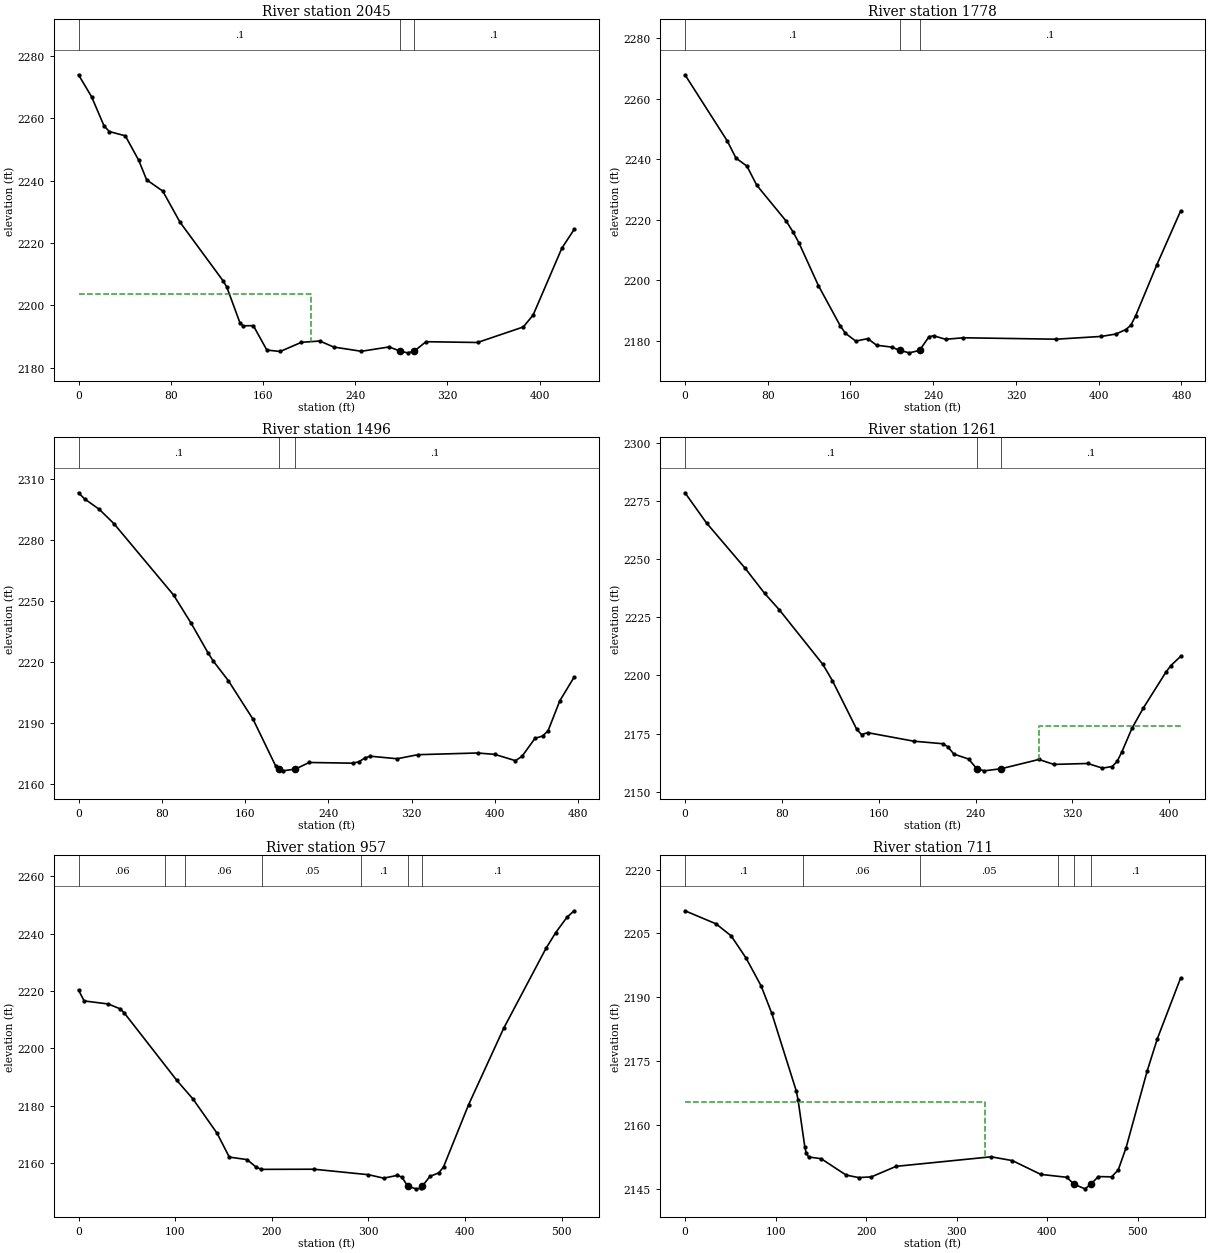
Type RM Length L Ch R = 1 ,2045    ,267.1,267.1,267.1
XS GIS Cut Line= 4
 2246312.6646741596908.2235572852246215.45656022596742.177247913
2246219.41450758596632.9379005992246129.24101044596541.616433477
#Sta/Elev= 30
       0 2273.92    11.4 2266.83    22.1 2257.56    26.7 2255.71    40.6 2254.34
    52.3 2246.44    59.1 2240.22    73.1  2236.6    88.1  2226.6   125.4 2207.83
   128.7 2205.78     140  2194.4   142.6 2193.38   151.7 2193.43   163.4  2185.6
     175 2185.15   193.4 2188.09   209.4  2188.5   221.4 2186.57   245.4 2185.21
   269.5  2186.6  279.09 2185.27   285.5 2184.71  291.38 2185.27   301.5 2188.28
   346.2 2188.03   385.9 2193.01   394.4  2196.8   419.4 2218.31430.0578 2224.32
#Mann= 3, -1 ,  0
       0     0.1       0  279.09   0.045       0  291.38     0.1       0
#XS Ineff= 2 , 0
          201.44 2203.62
Permanent Ineff=
       F       F
Bank Sta=279.09,291.38
XS Rating Curve= 0 ,0
Exp/Cntr(USF)=0,0
Exp/Cntr=0.3,0.1

Type RM Length L Ch R = 1 ,1778    ,282.2,282.2,282.2
XS GIS Cut Line= 2
2246561.99549741596803.5339577572246302.58579543 596400.66589965
#Sta/Elev= 30
       0 2267.99    40.9 2246.11    49.3 2240.46    59.9 2237.79    69.4 2231.47
      98 2219.56   104.3 2216.14   110.1 2212.49     129 2198.31   150.3  2184.9
     155 2182.58   165.1 2179.96   176.7 2180.78   185.3 2178.59   199.8 2177.98
  207.782176.871   216.9 2176.08  226.742176.873   235.9 2181.39   240.3 2181.73
   251.9 2180.56   269.2 2181.06     359 2180.59   402.6 2181.51   416.7  2182.3
   426.2 2183.78     431 2185.17   435.7 2188.32     456 2205.03   479.2 2222.99
#Mann= 3, -1 ,  0
       0     0.1       0  207.78   0.045       0  226.74     0.1       0
Bank Sta=207.78,226.74
XS Rating Curve= 0 ,0
Exp/Cntr(USF)=0,0
Exp/Cntr=0.3,0.1

Type RM Length L Ch R = 1 ,1496    ,235.2,235.2,235.2
XS GIS Cut Line= 4
2246799.34677412596649.6233732332246717.31374945596524.024779468
2246653.72272843596466.7664742342246500.13619978596281.759977096
#Sta/Elev= 30
       0 2303.39     5.8  2300.4      20  2295.2      34 2288.18    91.3 2252.99
   108.2 2239.05   124.7 2224.19   129.5 2220.38   143.9 2210.77   167.7 2191.68
   189.2 2168.87  192.142167.173   196.1 2166.32  208.262167.173   221.5 2170.44
   263.4  2170.1   269.1 2170.76   275.6 2172.82   280.4 2173.53     306 2172.28
   325.9 2174.28   383.2 2175.12   399.7 2174.44   419.6 2171.34   425.9 2173.45
   438.4 2182.37   445.6 2183.45   450.9 2186.02   462.2 2200.84     476 2212.54
#Mann= 3, -1 ,  0
       0     0.1       0  192.14   0.045       0  208.26     0.1       0
Bank Sta=192.14,208.26
XS Rating Curve= 0 ,0
Exp/Cntr(USF)=0,0
Exp/Cntr=0.3,0.1

Type RM Length L Ch R = 1 ,1261    ,304.1,304.1,304.1
XS GIS Cut Line= 4
2246893.96306911596566.9701128522246895.44213286596373.957673812
2246818.49963606596316.2508012092246802.61936871596197.136357362
#Sta/Elev= 30
       0 2278.45    17.8 2265.48    49.8 2245.97    65.8 2235.25    77.8 2228.28
   113.8 2204.82   121.8 2197.75   141.8 2176.95   145.8 2174.64   150.9 2175.45
     189 2171.79   213.1 2170.69   217.1 2169.37   222.1 2166.24   234.3 2164.12
     241 2159.98   247.1 2159.06  261.232159.978   292.3 2163.94   304.7 2161.82
   332.6 2162.22   344.8 2160.23   352.8 2160.91   356.9 2163.09   360.9 2167.27
   369.2 2177.36   378.5 2185.98   397.2 2201.43   401.3 2204.25409.3646 2208.21
#Mann= 3, -1 ,  0
       0     0.1       0     241   0.045       0  261.23     0.1       0
#XS Ineff= 2 , 0
                          292.42         2178.38
Permanent Ineff=
       F       F
Bank Sta=241,261.23
XS Rating Curve= 0 ,0
Exp/Cntr(USF)=0,0
Exp/Cntr=0.3,0.1

Type RM Length L Ch R = 1 ,957     ,245.9,245.9,245.9
XS GIS Cut Line= 4
2247223.38240098596546.7085851622247146.05291003596285.773513001
2247086.33079613596193.4757006162246990.79229131596104.210298356
#Sta/Elev= 30
       0 2220.33     5.8 2216.54    30.8 2215.47    43.3 2213.75    47.5 2212.29
   101.7 2188.88   118.4 2182.41   143.4 2170.45     156 2162.17   174.4  2161.3
     184 2158.62   189.3  2157.9   243.6 2157.95     300 2156.04   315.7 2154.84
     330 2155.82   334.7 2155.16  340.632152.053   349.1 2151.12   353.9 2151.33
  355.712152.054   363.6 2155.45   372.9  2156.7   377.7 2158.78   403.6 2180.41
   439.8 2206.94   483.6 2234.79   493.8 2240.35   505.5 2245.71512.8384 2247.92
#Mann= 7, -1 ,  0
       0    0.06       0      90     0.1       0     110    0.06       0
     190    0.05       0  292.15     0.1       0  340.63   0.045       0
  355.71     0.1       0
Bank Sta=340.63,355.71
XS Rating Curve= 0 ,0
Exp/Cntr(USF)=0,0
Exp/Cntr=0.3,0.1

Type RM Length L Ch R = 1 ,711     ,255.6,255.6,255.6
XS GIS Cut Line= 4
2247594.26815716596362.1072676142247338.14675637596092.951999518
2247263.22264985596041.9167385522247184.46679051596009.501179621
#Sta/Elev= 30
       0 2210.32    34.4 2207.24      51 2204.42    67.2 2199.29    84.1 2192.65
    95.9 2186.19   122.8 2168.03   124.9 2165.84   132.3 2154.86   133.8 2153.41
   136.5 2152.45   150.4 2152.03     178 2148.18   191.7  2147.6   205.8 2147.76
   233.2 2150.24   338.1 2152.48   361.5 2151.59   392.9 2148.35   421.7 2147.66
  429.712146.021   441.7 2144.95  448.19 2146.02   456.4 2147.83   471.2 2147.77
   478.5 2149.42   487.1 2154.61   510.5 2172.72   521.7 2180.27547.3615 2194.53
#Mann= 6, -1 ,  0
       0     0.1       0     130    0.06       0     260    0.05       0
  411.54     0.1       0  429.71   0.045       0  448.19     0.1       0
#XS Ineff= 2 , 0
          330.97 2165.38
Permanent Ineff=
       F       F
Bank Sta=429.71,448.19
XS Rating Curve= 0 ,0
Exp/Cntr(USF)=0,0
Exp/Cntr=0.3,0.1