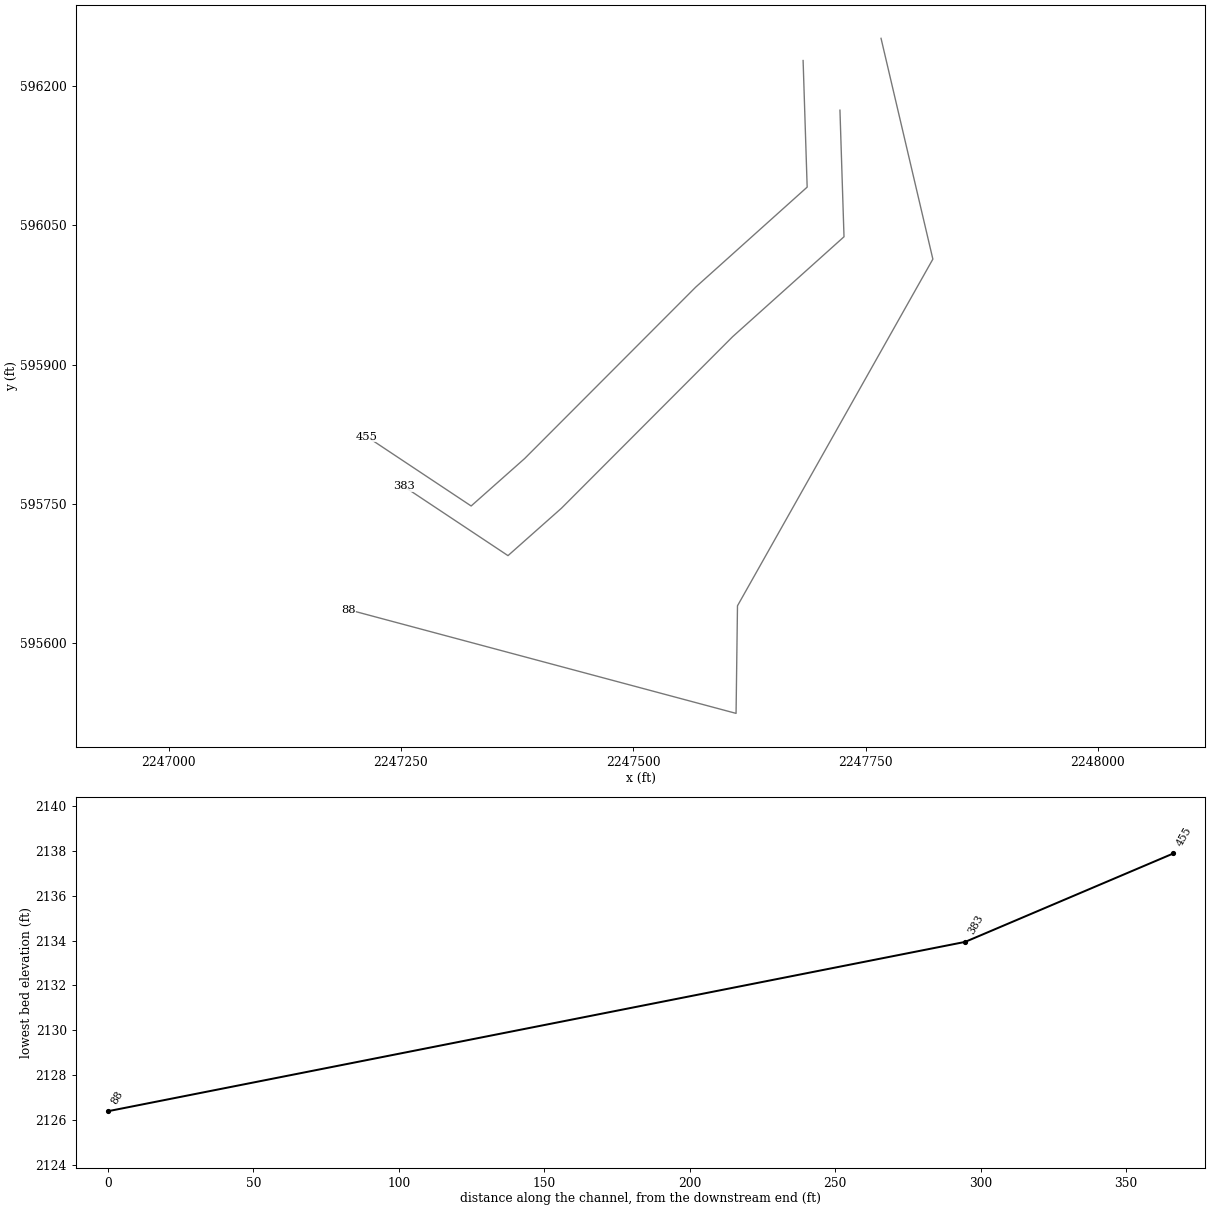
HEC-RAS study HAMILTRN1.prj: HAMILTRN1

--- HAMILTRN1.g01 (geometry) --- (continued)

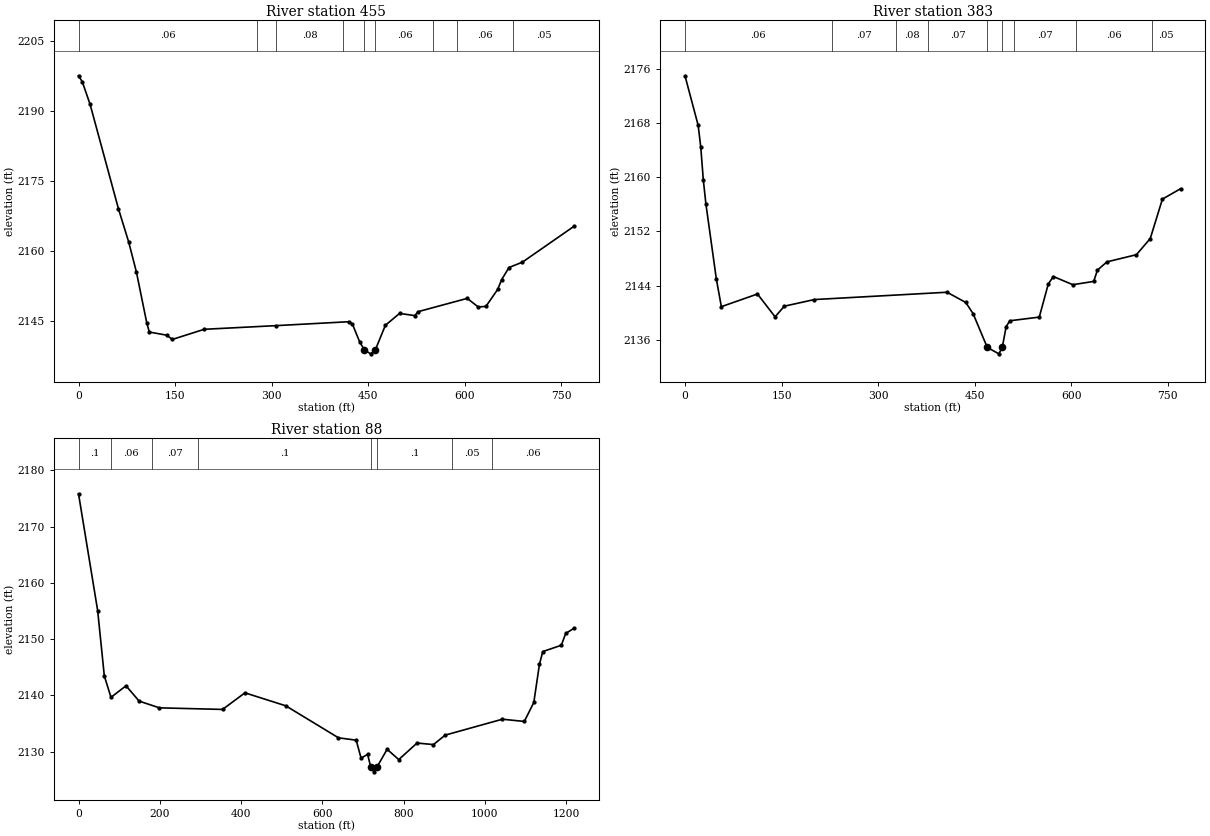
Type RM Length L Ch R = 1 ,455     ,71.6,71.6,71.6
XS GIS Cut Line= 6
2247682.82449331 596227.122841122247687.19350418596090.892517016
2247567.30876933595983.3244311662247383.15365162 595798.79708723
2247325.60325095595747.7618262642247213.17196593595822.459027757
#Sta/Elev= 30
       0 2197.59     5.9  2196.3      18 2191.45      62 2169.05      78 2161.87
      90 2155.42     106 2144.54     110 2142.56   136.8 2141.89   145.9 2140.98
   195.3 2143.15   307.4 2143.94   420.3 2144.78   425.6 2144.24   436.7 2140.47
  444.042138.722   453.8 2137.88   461.1 2138.72   476.7 2144.01   498.8 2146.56
   522.4 2146.09   527.4 2146.93   603.9 2149.79   620.8 2147.96   632.9 2148.06
   651.2 2151.72   657.3 2153.81   668.8 2156.42   689.6 2157.57     770 2165.29
#Mann= 9, -1 ,  0
       0    0.06       0  277.74    0.05       0   307.4    0.08       0
  411.47    0.06       0  444.04   0.045       0   461.1    0.06       0
  551.47    0.05       0  588.11    0.06       0  675.03    0.05       0
Bank Sta=444.04,461.1
XS Rating Curve= 0 ,0
Exp/Cntr(USF)=0,0
Exp/Cntr=0.3,0.1

Type RM Length L Ch R = 1 ,383     ,294.7,294.7,294.7
XS GIS Cut Line= 6
2247722.46920809 596173.694247052247726.83821897596037.463922946
2247606.95348412595929.895837096 2247422.7983664 595745.36849316
2247365.24796574595694.3332321942247252.81668072595769.030433687
#Sta/Elev= 30
       0 2174.97    20.5 2167.65    24.5 2164.46    28.5 2159.59    32.5 2156.07
    48.7    2145    56.5  2140.9   112.6 2142.77     140  2139.4   154.3 2140.97
     201 2141.95   407.1 2143.03   436.2 2141.52   447.6 2139.87  469.622134.886
   487.6 2133.94  492.872134.886     499 2137.97   504.7 2138.82   550.4 2139.36
   564.4 2144.25   572.3 2145.35   602.6 2144.14     635 2144.63   640.7 2146.29
   655.5 2147.51   701.3 2148.57   722.8 2150.95   741.7 2156.77     770 2158.31
#Mann= 9, -1 ,  0
       0    0.06       0  227.74    0.07       0   327.4    0.08       0
   377.4    0.07       0  469.62   0.045       0  492.87    0.06       0
  511.47    0.07       0  608.11    0.06       0  725.03    0.05       0
Bank Sta=469.62,492.87
XS Rating Curve= 0 ,0
Exp/Cntr(USF)=0,0
Exp/Cntr=0.3,0.1

Type RM Length L Ch R = 1 ,88      ,,,
XS GIS Cut Line= 5
2247766.68518983596251.0023442892247822.46049485  596013.4070575
2247612.21299647595640.3334365732247610.68091889595524.582024453
 2247193.5825679595636.173463857
#Sta/Elev= 30
       0 2175.85    47.1 2155.09    63.5 2143.46    79.9 2139.65   116.9  2141.7
   149.2 2138.98   199.1 2137.78   354.5  2137.5   409.6 2140.45   510.2 2138.14
   639.8 2132.45   683.4 2132.03   695.4 2128.83   711.5 2129.51  718.962127.301
   727.5  2126.4  734.882127.302   759.5 2130.41   788.1 2128.58   833.1 2131.52
   873.5 2131.25   902.4 2132.93  1043.2 2135.76  1097.1 2135.36  1120.5 2138.74
  1134.3 2145.51  1142.6 2147.79  1188.2 2148.91  1198.9 2151.01  1219.8 2151.95
#Mann= 8, -1 ,  0
       0     0.1       0      80    0.06       0     180    0.07       0
  294.05     0.1       0  718.96   0.045       0  734.88     0.1       0
  918.05    0.05       0 1018.05    0.06       0
Bank Sta=718.96,734.88
XS Rating Curve= 0 ,0
Exp/Cntr(USF)=0,0
Exp/Cntr=0.3,0.1
LCMann Table=0

Chan Stop Cuts=-1
Use User Specified Reach Order=0
Composite Channel Slope=5